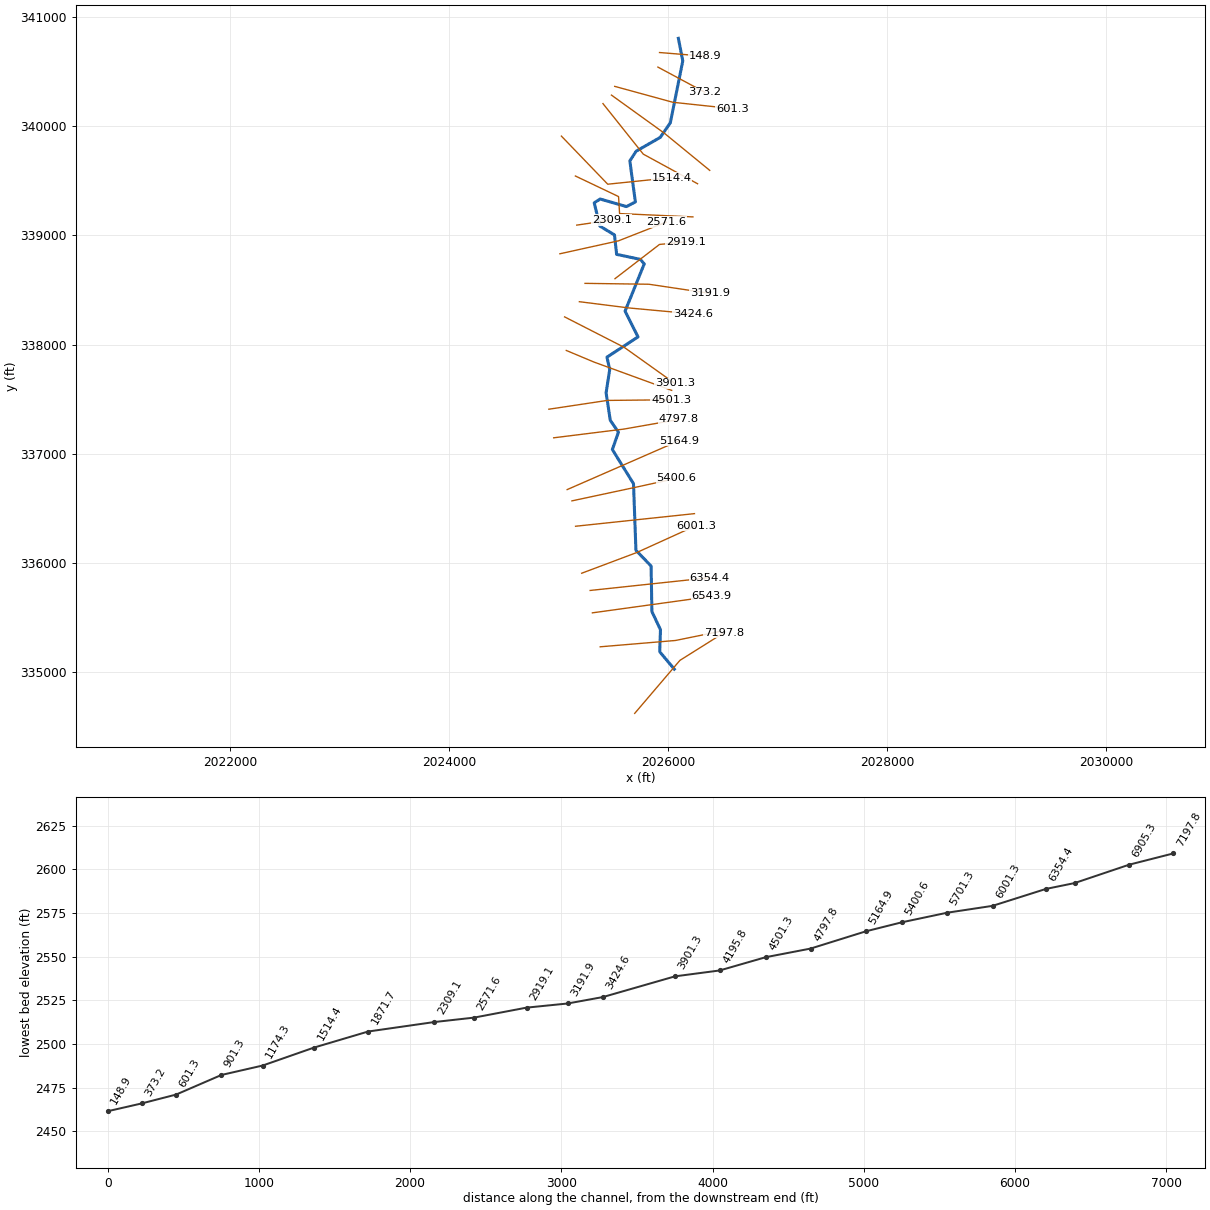
--- LittleCrk.prj (project) ---

Proj Title=LittleCrk
Current Plan=p01
Default Exp/Contr=0,0
English Units
Geom File=g01
Flow File=f01
Plan File=p01
BEGIN DESCRIPTION:
END DESCRIPTION:
DSS Export Rating Curves= 0
DSS Export Rating Curve Sorted= 0
DSS Export Volume Flow Curves= 0
DXF OffsetX= 0
DXF OffsetY= 0
DXF ScaleX= 0
DXF ScaleY= 0

--- LittleCrk.p01 (plan) ---

Plan Title=Floodplain
Program Version=4.00
Geom File=g01
Flow File=f01
K Sum by GR=0
Std Step Tol=0.01
Critical Tol=0.01
Num of Std Step Trials=20
Max Error Tol=0.3
Flow Tol Ratio=0.001
Split Flow NTrial=30
Split Flow Tol=0.02
Split Flow Ratio=0.02
Log Output Level=0
Friction Slope Method=1
Unsteady Friction Slope Method=2
Unsteady Bridges Friction Slope Method=1
Global Log Level=0
CheckData=False
Run HTab=0
Run UNet=0
Run PostProcess=0
UNET Theta=0
UNET Theta Warmup=0
UNET ZTol=0
UNET ZSATol=0
UNET MxIter=0
UNET MaxInSteps=0
UNET DtIC=0
UNET DtMin=0
UNET MaxCRTS=0
UNET WFStab=0
UNET SFStab=0
UNET WFX=0
UNET SFX=0
UNET DSS MLevel=0
UNET DZMax Abort=0
UNET Convert EG Bridges=0
UNET Use Existing IB Tables=0
UNET Froude Limit=0
UNET Froude Power=0
Write IC File=0
Echo Input=False
Echo Output=False
Write Detailed=0

--- LittleCrk.f01 (steady flow) ---

Flow Title=NFF Regression Equation
Program Version=4.00
Number of Profiles=1
Profile Names=P100yr
River Rch & RM=LittleCrk,Main      ,7197.8
521.3636
River Rch & RM=LittleCrk,Main      ,6905.3
524.6019
River Rch & RM=LittleCrk,Main      ,6543.9
582.3201
River Rch & RM=LittleCrk,Main      ,4501.3
639.5617
River Rch & RM=LittleCrk,Main      ,601.3
700.9209
Boundary for River Rch & Prof#=LittleCrk,Main      ,1
Up Type=0
Dn Type=3
Dn Slope=0.026497

--- LittleCrk.g01 (geometry) ---

Geom Title=USGS 3m DEM
Program Version=4.00

River Reach=LittleCrk     ,Main
Reach XY= 30
     2026055.266      335028.308     2025921.764      335187.871
     2025928.787      335389.442     2025850.406      335556.085
     2025843.129      335972.244     2025704.572      336116.849
     2025682.371      336726.324     2025489.294      337038.724
     2025544.850      337198.230     2025470.197      337306.085
     2025432.003      337557.821     2025464.864      337770.376
     2025439.933      337884.586     2025723.669      338070.024
     2025605.614      338306.085     2025780.474      338738.247
     2025744.953      338779.576     2025528.099      338825.511
     2025508.623      339003.597     2025374.602      339084.731
     2025323.351      339297.427     2025378.183      339332.127
     2025617.767      339262.682     2025699.414      339305.446
     2025649.017      339681.085     2025706.308      339769.627
     2025926.794      339896.363     2026018.808      340030.044
     2026132.527      340595.926     2026092.136      340802.939

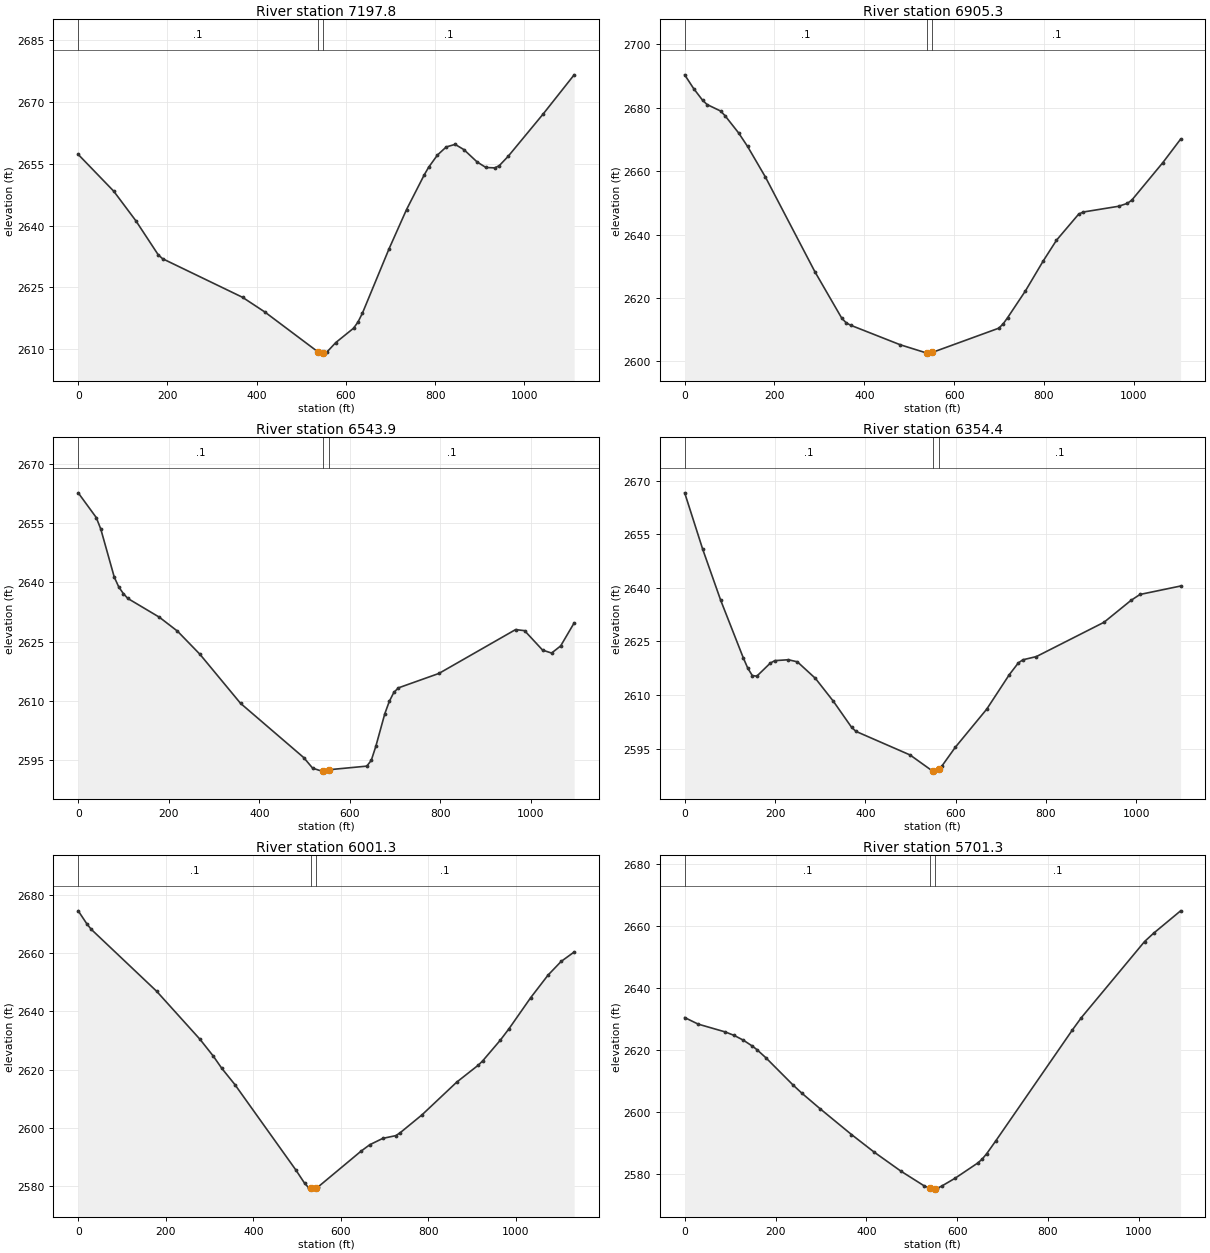
Type RM Length L Ch R = 1 ,7197.8,308.9,292.4,275.8
XS GIS Cut Line= 3
     2025693.347      334623.750     2026106.174      335108.832
     2026507.671      335361.649
#Sta/Elev= 30
       0 2657.26    79.6 2648.34   129.4 2641.13   179.2 2632.92   189.1 2631.95
   368.2 2622.59   418.0 2619.04   536.9 2609.38   547.4 2609.04   548.9 2609.08
   557.4 2609.31   577.2 2611.60   617.1 2615.09   627.0 2616.59   637.0 2618.76
   696.3 2634.29   735.8 2643.89   775.4 2652.29   785.2 2654.13   805.0 2657.11
   824.8 2659.08   844.6 2659.70   864.3 2658.43   894.0 2655.43   913.7 2654.09
   933.5 2654.00   943.4 2654.52   963.2 2656.76  1042.2 2667.11  1111.4 2676.58
#Mann= 3 , 0 , 0
       0     0.1       0   536.9   0.045       0   548.9     0.1       0
Bank Sta=   536.9,   548.9
Exp/Cntr=0.3,0.1

Type RM Length L Ch R = 1 ,6905.3,360.3,361.4,362.5
XS GIS Cut Line= 3
     2025377.962      335233.130     2026065.407      335291.011
     2026471.805      335373.819
#Sta/Elev= 30
       0 2690.42    20.0 2686.08    40.0 2682.38    50.0 2681.04    80.0 2679.00
    90.0 2677.50   120.0 2672.11   140.0 2667.84   180.0 2658.12   290.0 2628.29
   349.9 2613.62   359.9 2612.14   369.9 2611.39   479.9 2605.25   539.4 2602.61
   539.9 2602.60   551.4 2602.82   699.8 2610.48   709.6 2611.88   719.5 2613.84
   759.0 2622.25   798.5 2631.67   828.1 2638.22   877.5 2646.46   887.4 2647.12
   966.4 2648.94   986.1 2649.87   996.0 2650.90  1065.1 2662.74  1104.6 2670.13
#Mann= 3 , 0 , 0
       0     0.1       0   539.4   0.045       0   551.4     0.1       0
Bank Sta=   539.4,   551.4
Exp/Cntr=0.3,0.1

Type RM Length L Ch R = 1 ,6543.9,190.1,189.5,188.9
XS GIS Cut Line= 2
     2025306.933      335543.950     2026391.999      335694.337
#Sta/Elev= 30
       0 2662.78    39.8 2656.51    49.8 2653.59    79.7 2641.34    89.6 2638.86
    99.6 2637.20   109.5 2635.95   179.2 2631.18   219.1 2627.65   268.9 2621.75
   358.5 2609.30   497.9 2595.53   517.8 2592.83   537.8 2592.07   541.2 2592.14
   553.2 2592.42   637.4 2593.34   647.3 2594.81   657.3 2598.35   677.2 2606.66
   687.1 2609.79   697.1 2612.06   707.1 2613.22   796.7 2616.89   966.0 2628.03
   985.9 2627.76  1025.7 2622.82  1045.6 2622.07  1065.6 2623.88  1095.4 2629.73
#Mann= 3 , 0 , 0
       0     0.1       0   541.2   0.045       0   553.2     0.1       0
Bank Sta=   541.2,   553.2
Exp/Cntr=0.3,0.1

Type RM Length L Ch R = 1 ,6354.4,347.7,353,359.8
XS GIS Cut Line= 2
     2025286.293      335748.893     2026378.151      335865.789
#Sta/Elev= 30
       0 2666.60    39.9 2650.82    79.9 2636.48   129.8 2620.41   139.8 2617.51
   149.7 2615.47   159.7 2615.29   189.7 2618.96   199.6 2619.64   229.6 2619.89
   249.6 2619.30   289.5 2614.67   329.4 2608.24   369.4 2601.01   379.3 2599.84
   499.1 2593.24   549.0 2588.72   550.9 2588.75   562.9 2589.32   569.0 2590.05
   599.0 2595.36   668.8 2606.07   718.8 2615.72   738.7 2618.99   748.7 2619.87
   778.6 2620.77   928.4 2630.37   988.3 2636.51  1008.2 2638.16  1098.1 2640.52
#Mann= 3 , 0 , 0
       0     0.1       0   550.9   0.045       0   562.9     0.1       0
Bank Sta=   550.9,   562.9
Exp/Cntr=0.3,0.1

Type RM Length L Ch R = 1 ,6001.3,305.4,300,293.2
XS GIS Cut Line= 3
     2025208.898      335906.541     2025711.606      336095.747
     2026254.219      336342.765
#Sta/Elev= 30
       0 2674.48    19.9 2669.98    29.8 2668.13   179.0 2646.93   278.5 2630.38
   308.4 2624.71   328.2 2620.45   358.1 2614.88   497.4 2585.59   517.2 2581.09
   527.2 2579.43   531.1 2579.28   537.1 2579.04   543.1 2579.41   547.1 2579.66
   646.4 2592.07   666.3 2594.27   696.1 2596.45   725.9 2597.39   735.9 2598.40
   785.6 2604.51   865.0 2615.74   914.7 2621.61   924.7 2623.10   964.4 2630.09
   984.3 2634.02  1034.0 2644.70  1073.7 2652.45  1103.5 2657.11  1133.3 2660.36
#Mann= 3 , 0 , 0
       0     0.1       0   531.1   0.045       0   543.1     0.1       0
Bank Sta=   531.1,   543.1
Exp/Cntr=0.3,0.1

Type RM Length L Ch R = 1 ,5701.3,298.2,300.5,302.9
XS GIS Cut Line= 3
     2025153.131      336336.601     2025696.068      336394.362
     2026239.004      336452.122
#Sta/Elev= 30
       0 2630.45    29.8 2628.33    89.4 2625.81   109.2 2624.67   129.0 2623.17
   148.9 2621.26   158.8 2620.14   178.7 2617.50   238.2 2608.76   258.1 2606.05
   297.8 2601.09   367.3 2592.73   417.0 2587.08   476.5 2580.88   526.2 2576.28
     540 2575.34   546.0 2575.12     552 2575.27   555.9 2575.36   565.8 2576.09
   595.6 2578.65   645.3 2583.54   655.2 2584.83   665.1 2586.57   685.0 2590.68
   853.8 2626.48   873.6 2630.46  1012.6 2654.96  1032.4 2657.63  1092.0 2664.87
#Mann= 3 , 0 , 0
       0     0.1       0     540   0.045       0     552     0.1       0
Bank Sta=     540,     552
Exp/Cntr=0.3,0.1

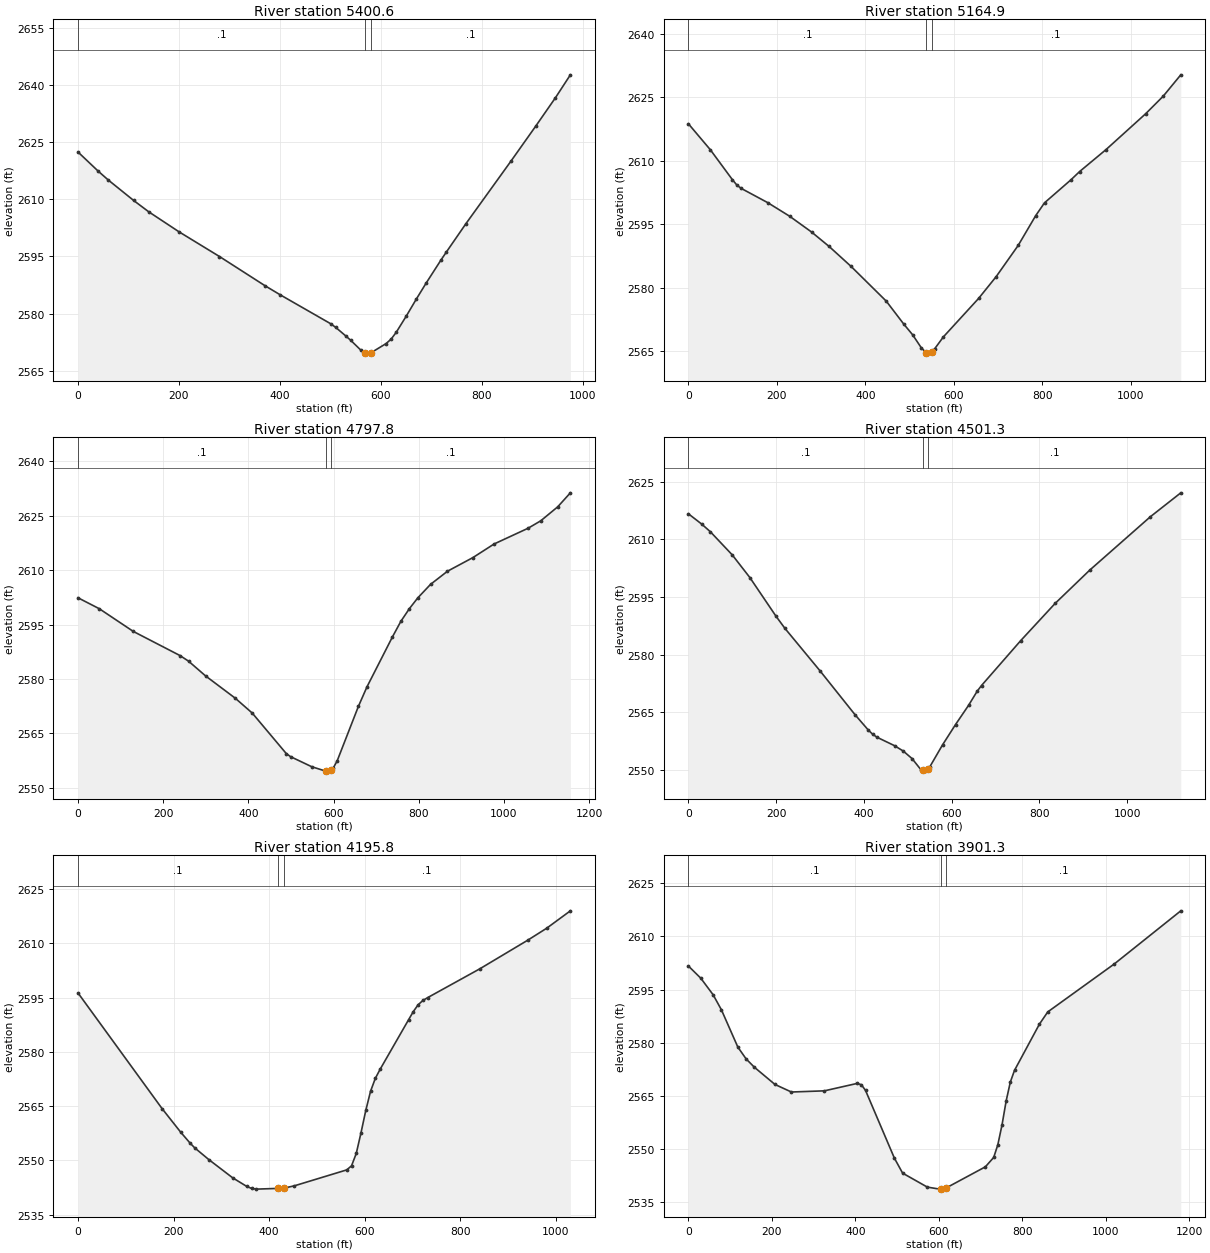
Type RM Length L Ch R = 1 ,5400.6,231.7,235.7,239.8
XS GIS Cut Line= 3
     2025119.831      336568.954     2025755.831      336705.125
     2026073.051      336775.194
#Sta/Elev= 30
       0 2622.40    40.0 2617.38    60.0 2615.05   110.1 2609.70   140.1 2606.71
   200.1 2601.46   280.2 2594.98   370.2 2587.33   400.2 2584.95   500.3 2577.35
   510.3 2576.39   530.3 2574.14   540.3 2572.97   560.4 2570.38   568.5 2569.76
   570.4 2569.62   580.5 2569.73   610.4 2572.14   620.4 2573.33   630.4 2575.10
   650.4 2579.38   670.1 2583.80   689.8 2588.05   719.3 2594.13   729.2 2596.07
   768.6 2603.64   857.2 2619.94   906.4 2629.15   945.8 2636.67   975.3 2642.67
#Mann= 3 , 0 , 0
       0     0.1       0   568.5   0.045       0   580.5     0.1       0
Bank Sta=   568.5,   580.5
Exp/Cntr=0.3,0.1

Type RM Length L Ch R = 1 ,5164.9,375.4,367,361
XS GIS Cut Line= 2
     2025076.176      336672.068     2026095.748      337118.370
#Sta/Elev= 30
       0 2618.68    49.7 2612.53    99.4 2605.48   109.3 2604.23   119.2 2603.43
   178.9 2600.08   228.6 2596.86   278.2 2593.13   318.0 2589.71   367.7 2584.99
   447.2 2576.79   486.9 2571.35   506.8 2568.84   526.7 2565.72   537.7 2564.61
   546.6 2564.51   549.7 2564.83   556.5 2565.52   576.4 2568.36   655.9 2577.43
   695.6 2582.58   745.3 2589.94   785.0 2596.99   804.9 2600.02   864.5 2605.44
   884.4 2607.42   944.0 2612.60  1033.5 2621.06  1073.2 2625.21  1113.0 2630.26
#Mann= 3 , 0 , 0
       0     0.1       0   537.7   0.045       0   549.7     0.1       0
Bank Sta=   537.7,   549.7
Exp/Cntr=0.3,0.1

Type RM Length L Ch R = 1 ,4797.8,293.4,296.4,294.1
XS GIS Cut Line= 3
     2024953.150      337146.209     2025596.583      337226.500
     2026096.301      337314.404
#Sta/Elev= 30
       0 2602.41    49.9 2599.40   129.7 2593.14   239.4 2586.48   259.4 2584.94
   299.3 2580.88   369.1 2574.72   409.0 2570.62   488.8 2559.46   498.8 2558.61
   548.7 2555.82   581.2 2554.62   588.6 2554.61   593.2 2554.95   598.6 2555.34
   608.5 2557.49   658.4 2572.53   678.3 2577.85   738.0 2591.61   757.9 2595.93
   777.8 2599.41   797.7 2602.40   827.5 2606.11   867.3 2609.74   927.0 2613.50
   976.7 2617.25  1056.3 2621.58  1086.2 2623.64  1126.0 2627.49  1155.8 2631.36
#Mann= 3 , 0 , 0
       0     0.1       0   581.2   0.045       0   593.2     0.1       0
Bank Sta=   581.2,   593.2
Exp/Cntr=0.3,0.1

Type RM Length L Ch R = 1 ,4501.3,330,305.4,296.8
XS GIS Cut Line= 3
     2024908.963      337407.902     2025442.476      337488.434
     2026024.955      337494.456
#Sta/Elev= 30
       0 2616.67    30.0 2614.02    50.0 2612.00    99.9 2605.97   139.9 2600.09
   199.8 2589.97   219.8 2586.86   299.8 2575.80   379.7 2564.36   409.7 2560.40
   419.7 2559.30   429.6 2558.51   469.6 2556.31   489.6 2554.90   509.6 2552.95
   529.6 2550.08   533.6 2549.92   539.6 2549.68   545.6 2550.29   549.4 2550.67
   579.0 2556.50   608.7 2561.81   638.3 2566.79   658.0 2570.48   667.9 2571.97
   756.8 2583.60   835.8 2593.36   914.7 2602.03  1053.0 2615.94  1122.1 2622.14
#Mann= 3 , 0 , 0
       0     0.1       0   533.6   0.045       0   545.6     0.1       0
Bank Sta=   533.6,   545.6
Exp/Cntr=0.3,0.1

Type RM Length L Ch R = 1 ,4195.8,267.4,294.4,294.3
XS GIS Cut Line= 3
     2025068.202      337945.978     2025320.449      337839.920
     2026031.306      337580.343
#Sta/Elev= 30
       0 2596.31   175.9 2564.34   215.0 2557.80   234.6 2554.79   244.3 2553.48
   273.6 2550.26   323.4 2545.23   353.3 2542.81   363.2 2542.28   373.2 2542.08
   418.2 2542.28   430.2 2542.33   452.9 2543.00   562.4 2547.40   572.4 2548.53
   582.3 2551.94   592.3 2557.71   602.2 2563.83   612.2 2569.14   622.2 2572.71
   632.1 2575.19   691.8 2588.92   701.8 2591.19   711.8 2593.06   721.7 2594.24
   731.7 2595.03   841.2 2603.02   940.8 2610.88   980.6 2614.20  1030.4 2619.03
#Mann= 3 , 0 , 0
       0     0.1       0   418.2   0.045       0   430.2     0.1       0
Bank Sta=   418.2,   430.2
Exp/Cntr=0.3,0.1

Type RM Length L Ch R = 1 ,3901.3,484.2,476.5,482.9
XS GIS Cut Line= 3
     2025053.108      338253.128     2025597.721      337974.133
     2026059.709      337643.942
#Sta/Elev= 30
       0 2601.62    29.6 2598.19    59.2 2593.51    79.0 2589.28   118.4 2578.76
   138.2 2575.44   157.9 2573.10   207.3 2568.24   246.7 2566.11   325.7 2566.44
   404.6 2568.54   414.5 2568.15   424.4 2566.54   493.5 2547.46   513.2 2543.24
   572.4 2539.30   602.0 2538.73   605.9 2538.74   617.9 2539.09   711.5 2545.02
   731.5 2547.67   741.4 2551.26   751.4 2556.84   761.4 2563.65   771.3 2568.91
   781.3 2572.21   841.0 2585.24   861.0 2588.69  1020.4 2602.21  1179.8 2617.19
#Mann= 3 , 0 , 0
       0     0.1       0   605.9   0.045       0   617.9     0.1       0
Bank Sta=   605.9,   617.9
Exp/Cntr=0.3,0.1

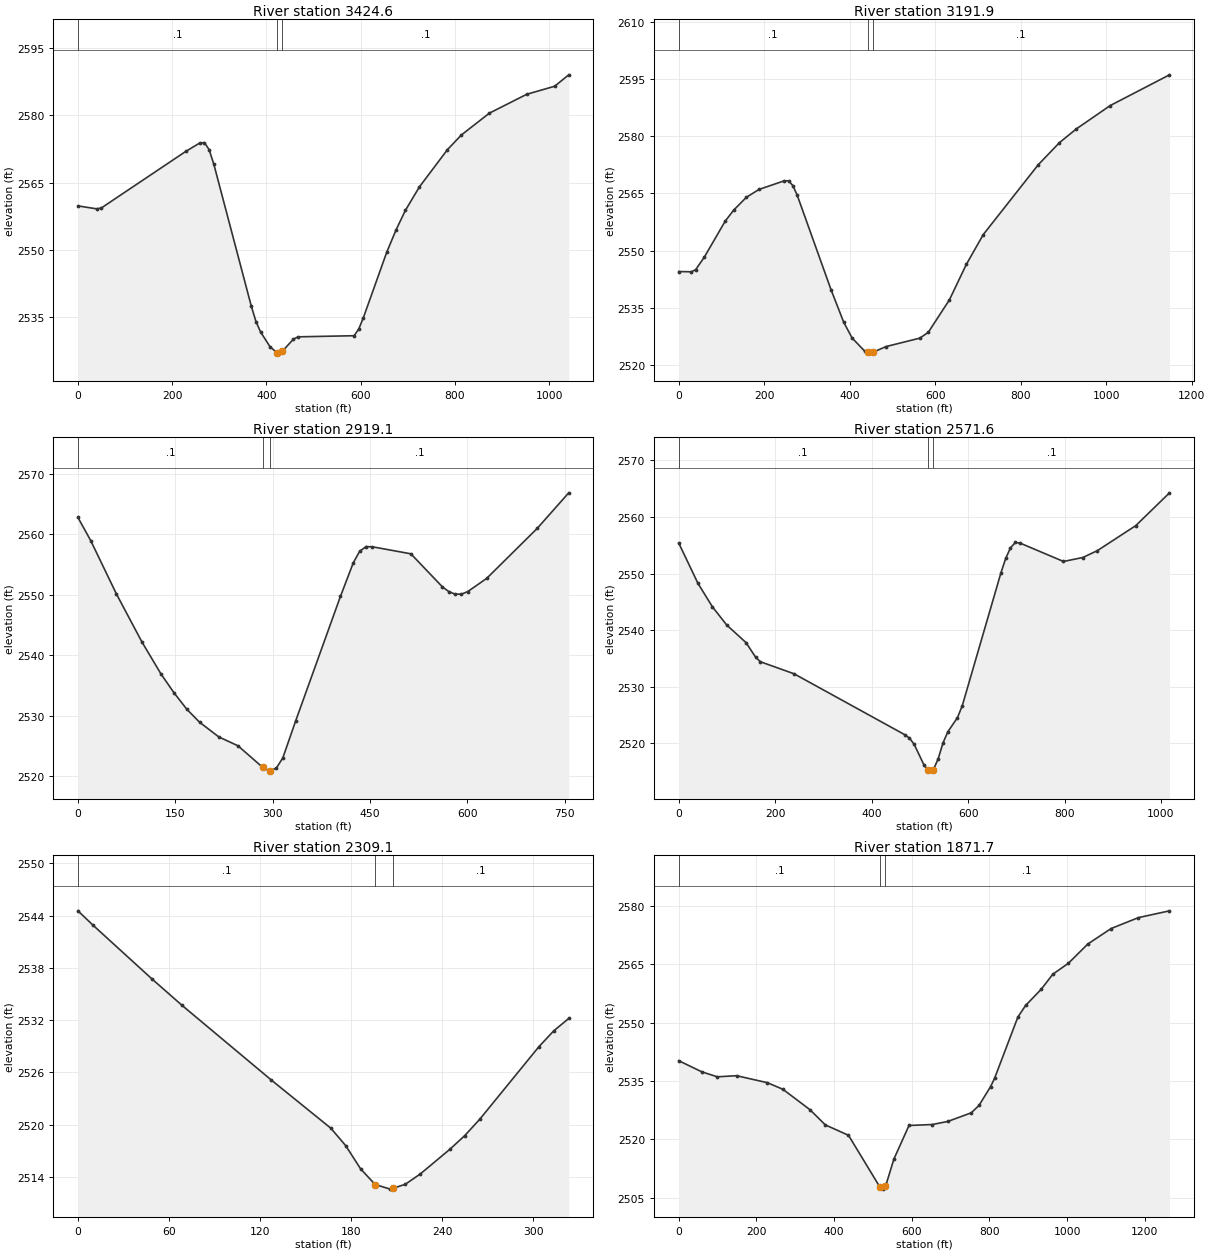
Type RM Length L Ch R = 1 ,3424.6,229.9,232.7,235.6
XS GIS Cut Line= 3
     2025187.637      338392.188     2025641.491      338334.860
     2026223.292      338280.943
#Sta/Elev= 30
       0 2559.78    39.8 2559.12    49.7 2559.32   228.7 2571.94   258.6 2573.83
   268.5 2573.91   278.4 2572.36   288.4 2569.10   368.0 2537.37   377.9 2533.94
   387.8 2531.60   407.7 2528.32   422.1 2527.03   427.6 2526.89   434.1 2527.33
   457.5 2530.03   467.4 2530.53   586.2 2530.78   596.1 2532.28   606.0 2534.84
   655.5 2549.43   675.3 2554.42   695.1 2558.78   724.8 2564.02   784.3 2572.34
   814.0 2575.63   873.4 2580.50   952.6 2584.71  1012.0 2586.51  1041.8 2589.06
#Mann= 3 , 0 , 0
       0     0.1       0   422.1   0.045       0   434.1     0.1       0
Bank Sta=   422.1,   434.1
Exp/Cntr=0.3,0.1

Type RM Length L Ch R = 1 ,3191.9,260.5,272.8,286.3
XS GIS Cut Line= 3
     2025239.742      338560.021     2025823.262      338551.968
     2026381.455      338468.491
#Sta/Elev= 30
       0 2544.56    29.7 2544.50    39.6 2545.06    59.4 2548.25   108.8 2557.77
   128.6 2560.64   158.3 2564.00   187.9 2566.06   247.3 2568.33   257.2 2568.28
   267.1 2567.04   277.0 2564.59   356.1 2539.86   385.8 2531.33   405.5 2527.18
   435.2 2523.71   441.8 2523.38   445.1 2523.21   453.8 2523.40   484.7 2524.92
   563.8 2527.13   583.6 2528.63   633.1 2537.14   672.7 2546.42   712.3 2554.23
   841.0 2572.52   890.5 2578.29   930.1 2581.90  1009.4 2588.01  1148.0 2596.05
#Mann= 3 , 0 , 0
       0     0.1       0   441.8   0.045       0   453.8     0.1       0
Bank Sta=   441.8,   453.8
Exp/Cntr=0.3,0.1

Type RM Length L Ch R = 1 ,2919.1,355.2,347.4,338.5
XS GIS Cut Line= 3
     2025513.138      338602.713     2025919.537      338916.111
     2026161.592      338940.317
#Sta/Elev= 30
       0 2562.79    19.7 2558.96    59.2 2550.16    98.7 2542.18   128.3 2536.85
   148.0 2533.80   167.8 2531.07   187.5 2528.92   217.1 2526.49   246.7 2525.02
   284.6 2521.47   296.1 2520.83   296.6 2520.86   306.0 2521.36   315.8 2523.02
   335.6 2529.14   404.6 2549.73   424.4 2555.29   434.2 2557.19   444.1 2557.97
   454.0 2557.94   513.2 2556.78   561.9 2551.30   571.6 2550.54   581.3 2550.11
   591.0 2550.10   600.8 2550.53   630.0 2552.71   707.8 2560.97   756.5 2566.87
#Mann= 3 , 0 , 0
       0     0.1       0   284.6   0.045       0   296.6     0.1       0
Bank Sta=   284.6,   296.6
Exp/Cntr=0.3,0.1

Type RM Length L Ch R = 1 ,2571.6,263.9,262.3,260.8
XS GIS Cut Line= 3
     2025009.917      338830.755     2025544.987      338949.235
     2025981.961      339121.222
#Sta/Elev= 30
       0 2555.39    39.9 2548.27    69.8 2544.14    99.6 2540.91   139.5 2537.82
   159.4 2535.24   169.4 2534.43   239.1 2532.31   468.3 2521.57   478.3 2520.97
   488.2 2519.85   508.2 2516.27   516.2 2515.34   518.1 2515.12   528.2 2515.39
   538.1 2517.34   548.0 2520.11   558.0 2522.07   578.0 2524.57   588.0 2526.69
   667.9 2550.08   677.9 2552.67   687.9 2554.55   697.9 2555.49   707.9 2555.38
   797.8 2552.14   837.8 2552.84   867.8 2554.04   947.7 2558.47  1017.6 2564.26
#Mann= 3 , 0 , 0
       0     0.1       0   516.2   0.045       0   528.2     0.1       0
Bank Sta=   516.2,   528.2
Exp/Cntr=0.3,0.1

Type RM Length L Ch R = 1 ,2309.1,472.7,437.4,402.1
XS GIS Cut Line= 2
     2025164.068      339093.194     2025483.837      339140.331
#Sta/Elev= 19
       0 2544.54     9.8 2542.91    49.0 2536.68    68.6 2533.68   127.3 2525.12
   166.5 2519.59   176.3 2517.59   186.1 2514.93   195.7 2513.12   205.7 2512.59
   207.7 2512.70   215.5 2513.14   225.3 2514.31   244.9 2517.16   254.7 2518.73
   264.5 2520.59   303.6 2528.95   313.4 2530.77   323.2 2532.18
#Mann= 3 , 0 , 0
       0     0.1       0   195.7   0.045       0   207.7     0.1       0
Bank Sta=   195.7,   207.7
Exp/Cntr=0.3,0.1

Type RM Length L Ch R = 1 ,1871.7,323.2,357.2,391.3
XS GIS Cut Line= 4
     2025151.329      339542.908     2025545.809      339354.486
     2025555.179      339198.934     2026225.366      339168.394
#Sta/Elev= 30
       0 2540.23    59.6 2537.36    99.4 2536.08   149.0 2536.37   228.5 2534.56
   268.3 2532.87   337.8 2527.63   377.6 2523.70   437.2 2521.03   518.2 2507.68
   524.8 2507.17   530.2 2507.92   534.6 2508.53   554.0 2514.88   593.0 2523.55
   653.1 2523.80   693.1 2524.60   753.2 2526.81   773.2 2528.70   803.3 2533.58
   813.3 2535.67   873.4 2551.46   893.4 2554.46   933.4 2558.60   963.5 2562.50
  1003.5 2565.31  1053.6 2570.27  1113.7 2574.26  1183.8 2577.06  1263.9 2578.81
#Mann= 3 , 0 , 0
       0     0.1       0   518.2   0.045       0   530.2     0.1       0
Bank Sta=   518.2,   530.2
Exp/Cntr=0.3,0.1

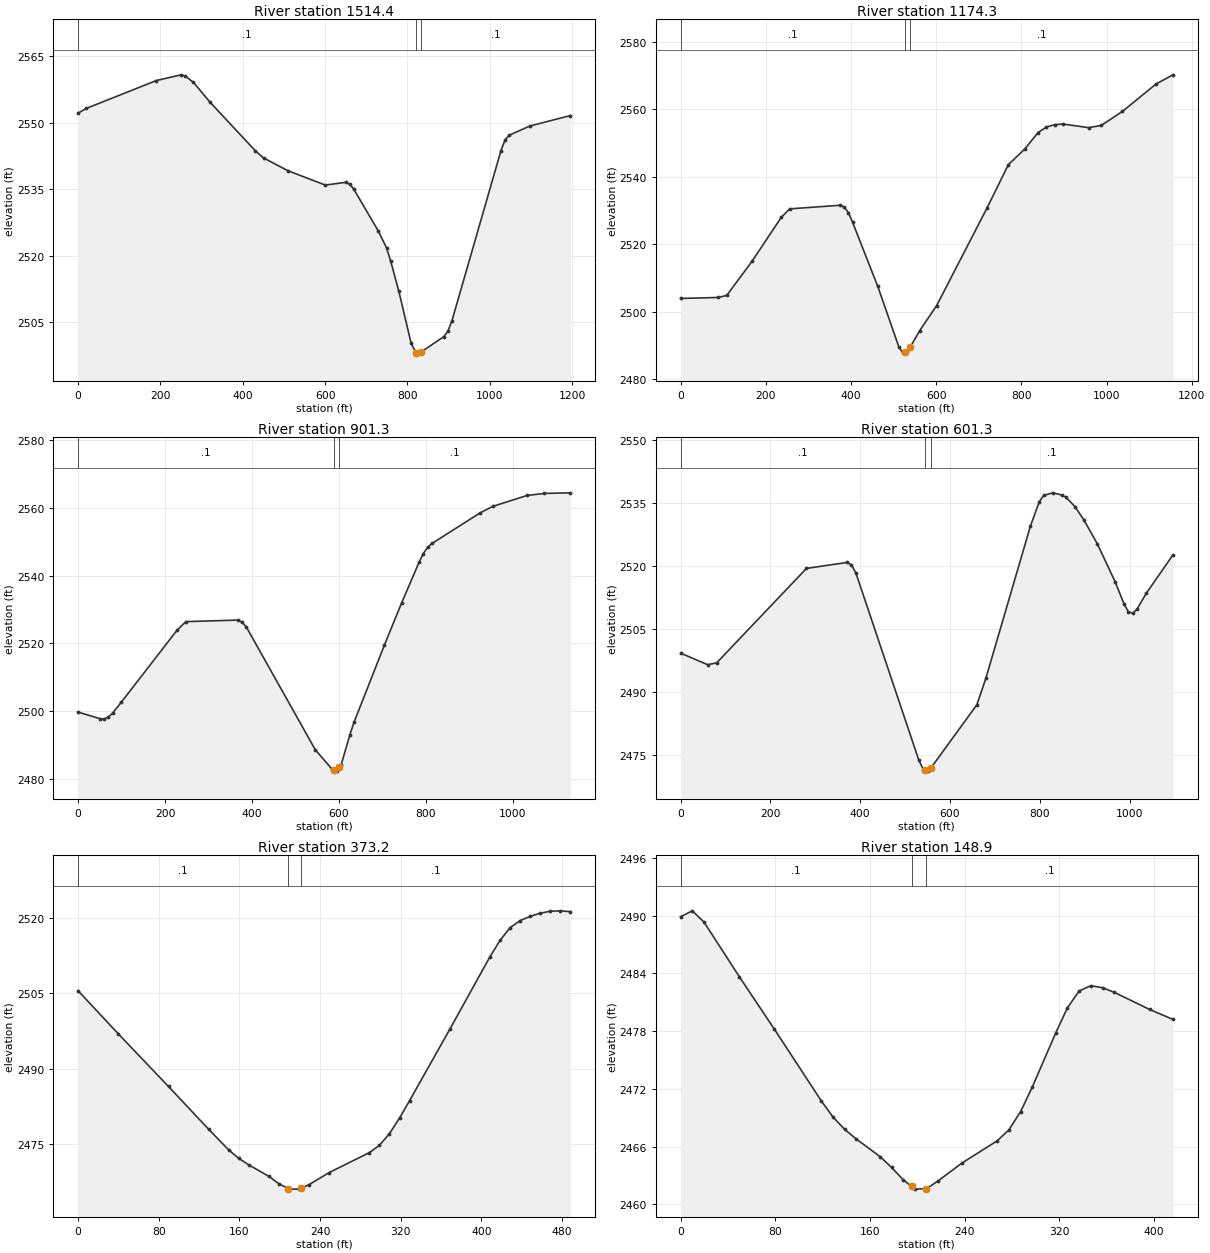
Type RM Length L Ch R = 1 ,1514.4,361.2,340.2,319.1
XS GIS Cut Line= 3
     2025023.695      339907.961     2025446.891      339467.743
     2026029.099      339527.620
#Sta/Elev= 30
       0 2552.16    20.0 2553.24   190.2 2559.53   250.3 2560.82   260.3 2560.55
   280.3 2559.12   320.3 2554.67   430.4 2543.70   450.5 2542.06   510.5 2539.15
   600.6 2535.94   650.3 2536.56   660.2 2536.13   670.2 2534.94   729.7 2525.51
   749.5 2521.72   759.4 2518.77   779.3 2511.92   809.0 2500.24   820.3 2498.15
   828.9 2498.01   832.3 2498.21   888.4 2501.73   898.3 2502.96   908.2 2505.34
  1027.3 2543.74  1037.2 2546.14  1047.1 2547.18  1096.7 2549.25  1195.9 2551.63
#Mann= 3 , 0 , 0
       0     0.1       0   820.3   0.045       0   832.3     0.1       0
Bank Sta=   820.3,   832.3
Exp/Cntr=0.3,0.1

Type RM Length L Ch R = 1 ,1174.3,267.1,272.9,277.4
XS GIS Cut Line= 3
     2025403.610      340205.362     2025771.755      339742.922
     2026267.499      339471.946
#Sta/Elev= 30
       0 2503.93    88.7 2504.23   108.4 2504.85   167.5 2514.91   236.4 2527.98
   256.1 2530.50   374.4 2531.56   384.2 2531.05   394.1 2529.36   403.9 2526.48
   463.0 2507.49   512.3 2489.59   522.1 2487.72     527 2487.96   532.0 2488.21
     539 2489.46   561.5 2494.42   601.0 2501.78   719.9 2530.87   769.5 2543.60
   809.1 2548.38   838.9 2553.09   858.7 2554.75   878.5 2555.48   898.4 2555.64
   957.8 2554.58   987.6 2555.23  1037.1 2559.37  1116.4 2567.54  1156.0 2570.24
#Mann= 3 , 0 , 0
       0     0.1       0     527   0.045       0     539     0.1       0
Bank Sta=     527,     539
Exp/Cntr=0.3,0.1

Type RM Length L Ch R = 1 ,901.3,292.4,300,312.2
XS GIS Cut Line= 3
     2025480.803      340283.471     2025963.254      339935.166
     2026378.454      339594.420
#Sta/Elev= 30
       0 2499.75    49.6 2497.83    59.5 2497.65    69.4 2498.22    79.3 2499.42
    99.2 2502.61   228.1 2523.97   247.9 2526.42   366.9 2526.88   376.9 2526.28
   386.8 2524.88   545.4 2488.66   585.1 2482.74     589 2482.57   595.0 2482.32
     601 2483.43   605.0 2484.17   624.9 2492.98   634.8 2496.80   704.4 2519.49
   744.2 2531.99   784.0 2543.90   794.0 2546.51   803.9 2548.35   813.9 2549.49
   923.3 2558.40   953.1 2560.40  1032.7 2563.65  1072.5 2564.24  1132.2 2564.42
#Mann= 3 , 0 , 0
       0     0.1       0     589   0.045       0     601     0.1       0
Bank Sta=     589,     601
Exp/Cntr=0.3,0.1

Type RM Length L Ch R = 1 ,601.3,233,228.2,219.9
XS GIS Cut Line= 3
     2025510.675      340363.336     2026041.730      340217.680
     2026584.342      340159.531
#Sta/Elev= 30
       0 2499.21    60.1 2496.46    80.1 2496.87   280.3 2519.39   370.4 2520.80
   380.5 2520.23   390.5 2518.24   530.6 2473.67   540.7 2471.45   544.7 2471.31
   550.7 2471.10   556.7 2471.75   659.8 2486.92   679.7 2493.19   778.9 2529.44
   798.7 2535.28   808.6 2536.77   828.5 2537.39   848.3 2536.89   858.3 2536.32
   878.1 2534.11   897.9 2530.95   927.7 2525.30   967.4 2516.25   987.2 2510.97
   997.2 2509.03  1007.1 2508.68  1017.0 2509.79  1036.8 2513.44  1096.4 2522.61
#Mann= 3 , 0 , 0
       0     0.1       0   544.7   0.045       0   556.7     0.1       0
Bank Sta=   544.7,   556.7
Exp/Cntr=0.3,0.1

Type RM Length L Ch R = 1 ,373.2,215.4,224.1,232.9
XS GIS Cut Line= 2
     2025904.950      340539.867     2026334.972      340308.836
#Sta/Elev= 30
       0 2505.52    39.8 2496.96    89.7 2486.45   129.5 2477.94   149.4 2473.82
   159.4 2472.14   169.4 2470.84   189.3 2468.55   199.2 2467.08   208.6 2466.10
   209.2 2466.04   219.2 2466.02   220.6 2466.15   229.1 2466.92   249.1 2469.33
   288.9 2473.29   298.9 2474.75   308.8 2477.08   318.8 2480.19   328.8 2483.66
   368.6 2497.85   408.4 2512.27   418.4 2515.54   428.4 2518.07   438.3 2519.46
   448.3 2520.33   458.3 2520.95   468.2 2521.34   478.2 2521.42   488.2 2521.26
#Mann= 3 , 0 , 0
       0     0.1       0   208.6   0.045       0   220.6     0.1       0
Bank Sta=   208.6,   220.6
Exp/Cntr=0.3,0.1

Type RM Length L Ch R = 1 ,148.9,143,148.9,154.8
XS GIS Cut Line= 2
     2025920.128      340673.089     2026334.972      340639.362
#Sta/Elev= 30
       0 2489.90     9.9 2490.51    19.8 2489.34    49.6 2483.67    79.3 2478.20
   118.9 2470.76   128.8 2469.08   138.7 2467.79   148.6 2466.78   168.5 2464.97
   178.4 2463.83   188.3 2462.54   195.2 2461.87   198.2 2461.58   207.2 2461.63
   208.1 2461.64   218.0 2462.47   237.8 2464.29   267.6 2466.60   277.5 2467.74
   287.4 2469.64   297.3 2472.20   317.1 2477.82   327.0 2480.43   336.9 2482.18
   346.8 2482.73   356.8 2482.51   366.7 2482.03   396.4 2480.26   416.2 2479.22
#Mann= 3 , 0 , 0
       0     0.1       0   195.2   0.045       0   207.2     0.1       0
Bank Sta=   195.2,   207.2
Exp/Cntr=0.3,0.1